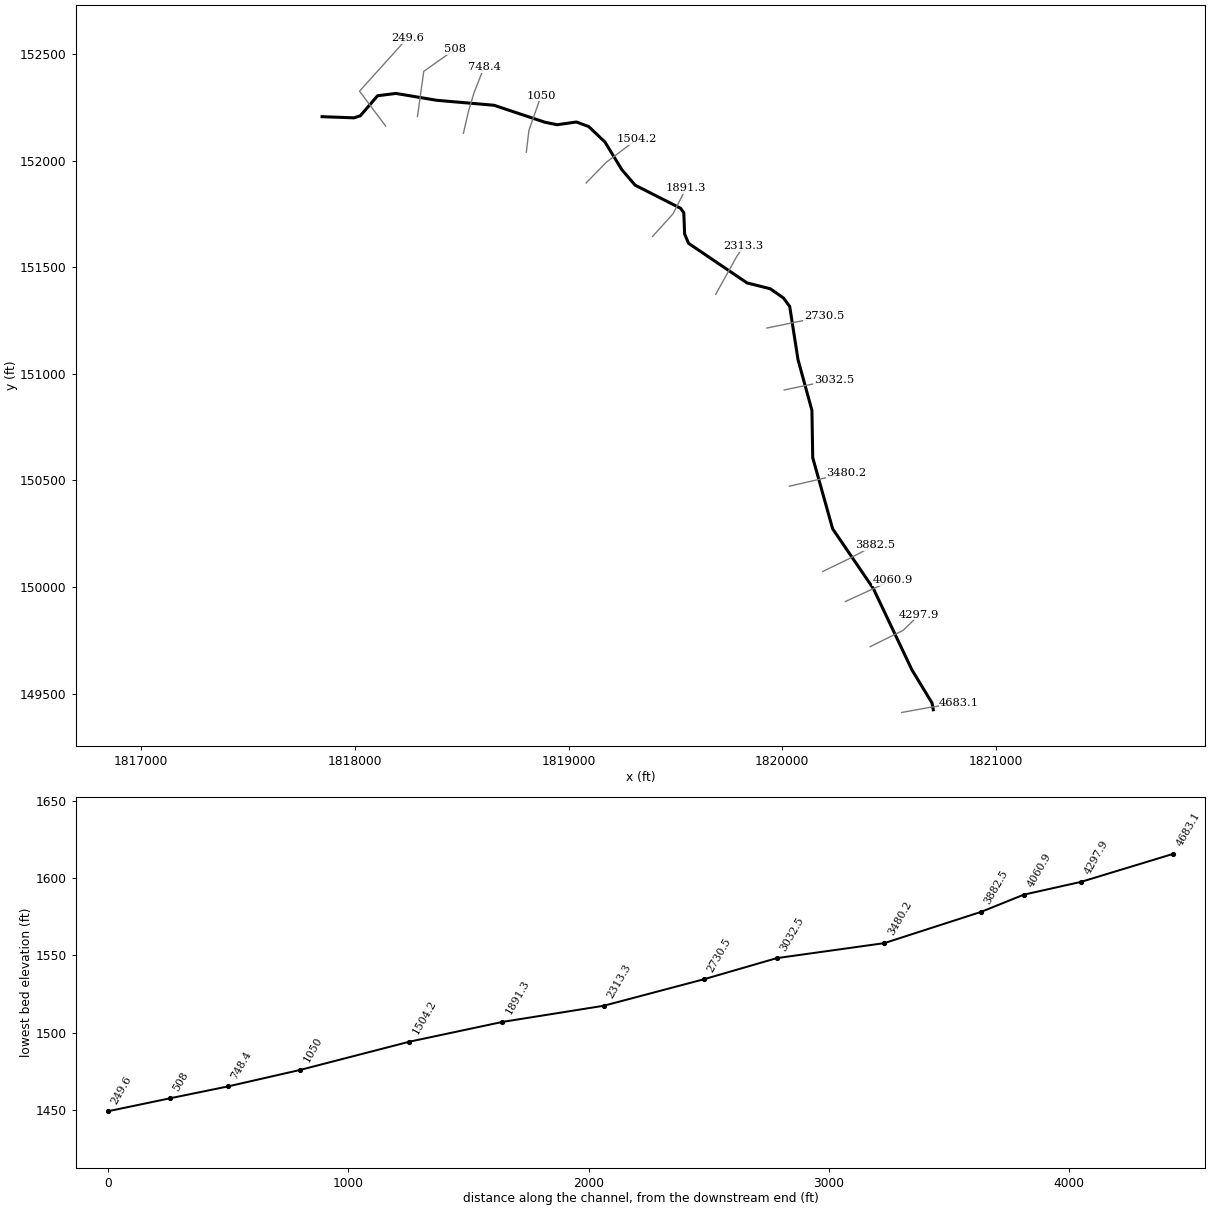
--- Upper Belcher Branch.prj (project) ---

Proj Title=Upper Belcher Branch
Current Plan=p01
Default Exp/Contr=0,0
English Units
Geom File=g01
Flow File=f01
Plan File=p01
BEGIN DESCRIPTION:
END DESCRIPTION:
DSS Export Rating Curves= 0
DSS Export Rating Curve Sorted= 0
DSS Export Volume Flow Curves= 0
DXF OffsetX= 0
DXF OffsetY= 0
DXF ScaleX= 0
DXF ScaleY= 0

--- Upper Belcher Branch.p01 (plan) ---

Plan Title=Floodplain
Program Version=4.00
Geom File=g01
Flow File=f01
K Sum by GR=0
Std Step Tol=0.01
Critical Tol=0.01
Num of Std Step Trials=20
Max Error Tol=0.3
Flow Tol Ratio=0.001
Split Flow NTrial=30
Split Flow Tol=0.02
Split Flow Ratio=0.02
Log Output Level=0
Friction Slope Method=1
Unsteady Friction Slope Method=2
Unsteady Bridges Friction Slope Method=1
Global Log Level=0
CheckData=False
Run HTab=0
Run UNet=0
Run PostProcess=0
UNET Theta=0
UNET Theta Warmup=0
UNET ZTol=0
UNET ZSATol=0
UNET MxIter=0
UNET MaxInSteps=0
UNET DtIC=0
UNET DtMin=0
UNET MaxCRTS=0
UNET WFStab=0
UNET SFStab=0
UNET WFX=0
UNET SFX=0
UNET DSS MLevel=0
UNET DZMax Abort=0
UNET Convert EG Bridges=0
UNET Use Existing IB Tables=0
UNET Froude Limit=0
UNET Froude Power=0
Write IC File=0
Echo Input=False
Echo Output=False
Write Detailed=0

--- Upper Belcher Branch.f01 (steady flow) ---

Flow Title=NFF Regression Equation
Program Version=4.00
Number of Profiles=1
Profile Names=P100yr
River Rch & RM=Upper Belcher...,Main      ,4683.1
553.4280
River Rch & RM=Upper Belcher...,Main      ,3032.5
590.3107
River Rch & RM=Upper Belcher...,Main      ,2730.5
714.1150
River Rch & RM=Upper Belcher...,Main      ,249.6
770.0621
Boundary for River Rch & Prof#=Upper Belcher...,Main      ,1
Up Type=0
Dn Type=3
Dn Slope=0.032993

--- Upper Belcher Branch.g01 (geometry) ---

Geom Title=Geometry
Program Version=4.00

River Reach=Upper Belcher...,Main
Reach XY= 30
     1820707.435      149425.002     1820701.559      149456.728
     1820607.422      149612.168     1820426.598      149993.726
      1820236.24      150273.387     1820143.021      150606.783
     1820139.292      150828.643     1820074.083      151066.546
     1820035.306      151315.656     1820005.931      151355.608
     1819944.139      151398.803     1819835.548      151426.111
     1819561.762      151611.768     1819543.334      151655.433
     1819539.436      151755.124      1819524.16      151776.275
     1819311.476       151884.38     1819249.199      151957.233
      1819170.47      152086.488     1819094.092      152159.341
     1819036.515      152180.492     1818946.655      152167.791
     1818889.634      152179.317     1818650.861      152259.043
     1818383.116      152282.292     1818191.654      152314.448
     1818105.838      152303.611     1818025.509      152209.982
     1817996.026      152200.021     1817845.968      152205.464

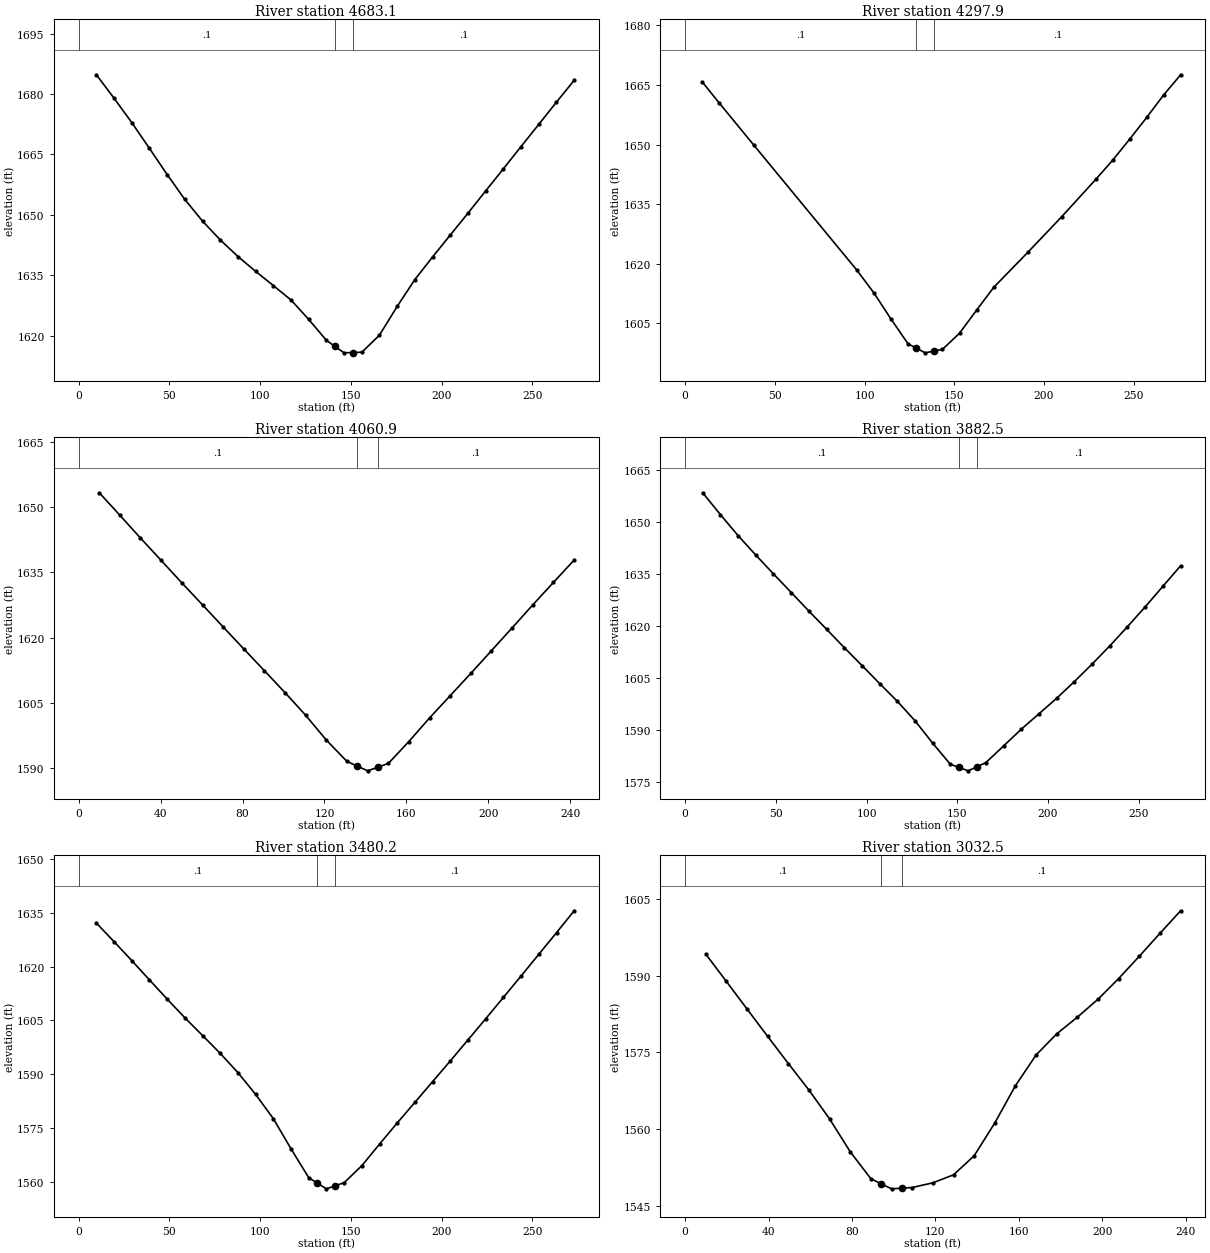
Type RM Length L Ch R = 1 ,4683.1  ,379.2,385.2,391.5
XS GIS Cut Line= 3
      1820559.07      149412.265     1820693.463      149436.706
     1820828.499      149456.526
#Sta/Elev= 30
     9.8 1684.76    19.5 1678.95    29.3 1672.88      39  1666.5    48.8 1659.98
    58.5 1653.82    68.3 1648.42    78.1 1643.74    87.8 1639.64    97.6 1635.93
   107.3 1632.43   117.1 1628.82   126.8 1624.02   136.6  1618.8   141.3 1617.31
   146.3 1615.72   151.3  1615.8   156.1 1615.88   165.8 1620.12   175.6 1627.28
   185.3 1633.92   195.1 1639.54   204.8 1644.96   214.6 1650.41   224.3 1655.91
   234.1 1661.42   243.8 1666.93   253.6 1672.45   263.3 1677.94   273.1 1683.39
#Mann= 3 , 0 , 0
       0      .1       0   141.3    .045       0   151.3      .1       0
Bank Sta=141.3,151.3
XS Rating Curve= 0 ,0
Exp/Cntr=0.3,0.1

Type RM Length L Ch R = 1 ,4297.9  ,237.6,237,236.4
XS GIS Cut Line= 3
     1820412.295      149721.091     1820566.429      149797.493
     1820641.153      149869.929
#Sta/Elev= 22
     9.6 1665.74    19.1 1660.42    38.2  1649.9    95.6 1618.42   105.1  1612.7
   114.7 1606.07   124.2 1599.83   128.8 1598.73   133.8 1597.54   138.8    1598
   143.4 1598.42   152.9 1602.48   162.5 1608.35     172 1614.05     191 1622.88
   209.9 1631.85   228.8 1641.22   238.3 1646.09   247.7 1651.35   257.2 1656.83
   266.6 1662.47   276.1 1667.57
#Mann= 3 , 0 , 0
       0      .1       0   128.8    .045       0   138.8      .1       0
Bank Sta=128.8,138.8
XS Rating Curve= 0 ,0
Exp/Cntr=0.3,0.1

Type RM Length L Ch R = 1 ,4060.9  ,177.4,178.4,179.5
XS GIS Cut Line= 2
     1820296.167      149932.623     1820515.902      150033.677
#Sta/Elev= 26
    10.1 1653.36    20.2 1648.15    30.2 1642.93    40.3 1637.78    50.4  1632.6
    60.5 1627.53    70.5 1622.49    80.6 1617.41    90.7 1612.38   100.8 1607.31
   110.9 1602.08   120.9 1596.41     131 1591.48   136.1 1590.39   141.1 1589.32
   146.1 1590.16   151.2 1591.03   161.2 1596.07   171.3  1601.5   181.4 1606.64
   191.5 1611.79   201.5 1616.98   211.6 1622.24   221.7 1627.54   231.8 1632.73
   241.9 1637.87
#Mann= 3 , 0 , 0
       0      .1       0   136.1    .045       0   146.1      .1       0
Bank Sta=136.1,146.1
XS Rating Curve= 0 ,0
Exp/Cntr=0.3,0.1

Type RM Length L Ch R = 1 ,3882.5  ,407.4,402.3,397.1
XS GIS Cut Line= 3
     1820190.129      150073.421     1820312.878      150133.091
     1820433.616      150196.974
#Sta/Elev= 30
     9.7 1658.43    19.5 1652.11    29.2 1646.06      39 1640.43    48.7 1635.01
    58.5 1629.64    68.2 1624.29      78 1619.02    87.7 1613.74    97.5 1608.56
   107.2 1603.36     117 1598.22   126.7 1592.62   136.5 1586.11   146.2 1580.06
     151 1579.13     156 1578.16     161 1579.38   165.8 1580.55   175.5 1585.33
   185.3 1590.19     195 1594.62   204.8 1599.12   214.5 1603.91   224.3 1608.98
   234.1 1614.25   243.8 1619.78   253.6 1625.52   263.3 1631.42   273.1 1637.36
#Mann= 3 , 0 , 0
       0      .1       0     151    .045       0     161      .1       0
Bank Sta=151,161
XS Rating Curve= 0 ,0
Exp/Cntr=0.3,0.1

Type RM Length L Ch R = 1 ,3480.2  ,448.2,447.7,447.2
XS GIS Cut Line= 3
     1820033.912       150473.09     1820166.881      150503.939
     1820299.849      150534.787
#Sta/Elev= 30
     9.7 1632.16    19.5 1626.95    29.3 1621.65      39 1616.27    48.8 1610.91
    58.5 1605.72    68.3 1600.74      78 1595.77    87.8 1590.38    97.5 1584.34
   107.3 1577.54     117 1569.14   126.8 1561.08   131.5 1559.58   136.5 1557.98
   141.5 1558.86   146.3 1559.71     156 1564.43   165.8 1570.47   175.5 1576.35
   185.3 1582.13     195 1587.89   204.8 1593.68   214.5 1599.54   224.3 1605.44
     234 1611.38   243.8 1617.38   253.5  1623.4   263.3 1629.47     273 1635.55
#Mann= 3 , 0 , 0
       0      .1       0   131.5    .045       0   141.5      .1       0
Bank Sta=131.5,141.5
XS Rating Curve= 0 ,0
Exp/Cntr=0.3,0.1

Type RM Length L Ch R = 1 ,3032.5  ,302,302,301.9
XS GIS Cut Line= 2
     1820009.455      150924.365     1820242.115      150972.542
#Sta/Elev= 26
     9.9  1594.2    19.8 1588.84    29.7 1583.45    39.6 1578.09    49.5 1572.79
    59.4 1567.58    69.3 1561.94    79.2 1555.51    89.1 1550.23      94 1549.26
      99 1548.27     104  1548.4   108.9 1548.53   118.8 1549.45   128.7 1551.01
   138.6 1554.74   148.5 1561.16   158.4 1568.46   168.3 1574.46   178.2  1578.6
   188.1 1581.86     198 1585.37   207.9 1589.42   217.8 1593.78   227.7 1598.26
   237.6 1602.67
#Mann= 3 , 0 , 0
       0      .1       0      94    .045       0     104      .1       0
Bank Sta=94,104
XS Rating Curve= 0 ,0
Exp/Cntr=0.3,0.1

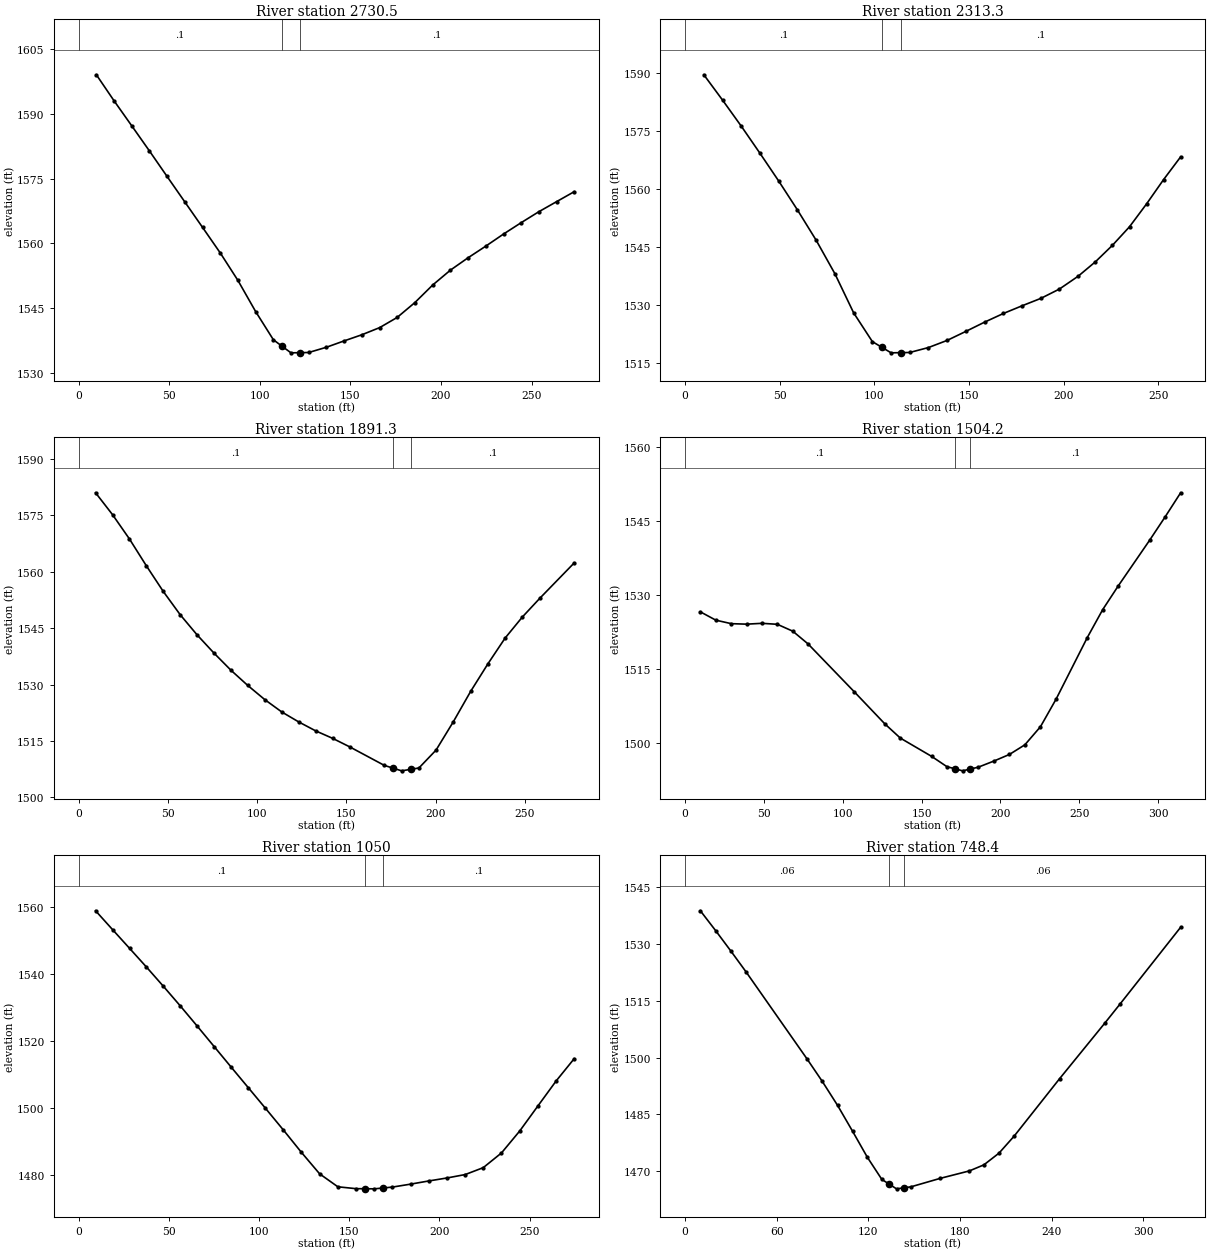
Type RM Length L Ch R = 1 ,2730.5  ,399.9,417.2,434.5
XS GIS Cut Line= 2
     1819928.377      151214.602     1820196.288      151269.829
#Sta/Elev= 30
     9.8 1599.01    19.5 1593.02    29.3 1587.21    39.1 1581.37    48.8 1575.49
    58.6 1569.59    68.4 1563.69    78.2 1557.76    87.9 1551.43    97.7 1544.21
   107.5 1537.68   112.2 1536.21   117.2 1534.66   122.2  1534.7     127 1534.74
   136.8 1535.96   146.5 1537.42   156.3 1538.84   166.1 1540.49   175.8 1542.85
   185.6  1546.3   195.4 1550.35   205.2  1553.8   214.9 1556.65   224.7 1559.35
   234.5 1562.15   244.2 1564.77     254 1567.32   263.8 1569.65   273.5 1571.95
#Mann= 3 , 0 , 0
       0      .1       0   112.2    .045       0   122.2      .1       0
Bank Sta=112.2,122.2
XS Rating Curve= 0 ,0
Exp/Cntr=0.3,0.1

Type RM Length L Ch R = 1 ,2313.3  ,421,421.9,422.9
XS GIS Cut Line= 3
     1819688.778      151372.744     1819789.721      151554.191
     1819820.272      151598.843
#Sta/Elev= 29
     9.9 1589.63    19.8 1583.05    29.7 1576.28    39.5  1569.3    49.4  1562.1
    59.3  1554.6    69.2 1546.73    79.1 1538.04      89 1527.89    98.9 1520.42
   103.8 1518.98   108.8 1517.51   113.8 1517.56   118.6  1517.6   128.5 1518.88
   138.4 1520.74   148.3 1523.08   158.2 1525.48   168.1 1527.72     178 1529.72
   187.9 1531.64   197.7 1534.06   207.6 1537.39   216.7 1541.13   225.7 1545.41
   234.7 1550.21   243.7 1556.14   252.7 1562.45   261.7 1568.34
#Mann= 3 , 0 , 0
       0      .1       0   103.8    .045       0   113.8      .1       0
Bank Sta=103.8,113.8
XS Rating Curve= 0 ,0
Exp/Cntr=0.3,0.1

Type RM Length L Ch R = 1 ,1891.3  ,396.3,387.2,378.1
XS GIS Cut Line= 3
      1819393.47       151643.98     1819488.616       151749.75
     1819550.275      151870.388
#Sta/Elev= 29
     9.5 1580.99      19 1575.17    28.5 1568.69    37.9 1561.61    47.4 1554.77
    56.9 1548.57    66.4 1543.19    75.9 1538.33    85.4 1533.78    94.8 1529.74
   104.3 1525.99   113.8 1522.71   123.3 1520.06   132.8 1517.68   142.3 1515.69
   151.9 1513.42   171.3 1508.49     176 1507.79     181 1507.04     186 1507.43
   190.7  1507.8   200.3 1512.56     210 1520.11   219.7 1528.18   229.4 1535.53
     239 1542.35   248.7 1547.97   258.4 1552.91   277.7 1562.33
#Mann= 3 , 0 , 0
       0      .1       0     176    .045       0     186      .1       0
Bank Sta=176,186
XS Rating Curve= 0 ,0
Exp/Cntr=0.3,0.1

Type RM Length L Ch R = 1 ,1504.2  ,442,454.2,466.3
XS GIS Cut Line= 3
     1819082.282      151894.802     1819177.562      151992.547
     1819319.702      152099.414
#Sta/Elev= 28
     9.7 1526.56    19.5 1524.87    29.3 1524.16      39 1524.06    48.8 1524.23
    58.5 1524.03    68.3 1522.63      78 1520.04   107.2 1510.35   126.7 1503.79
   136.5 1500.91   156.3  1497.2   166.1 1495.09     171 1494.68     176 1494.25
     181 1494.62   185.9 1494.99   195.8 1496.23   205.7 1497.58   215.5 1499.54
   225.4 1503.22   235.3 1508.82   255.1 1521.34   264.9 1527.03   274.8 1531.87
   294.6  1541.1   304.5 1545.88   314.3 1550.76
#Mann= 3 , 0 , 0
       0      .1       0     171    .045       0     181      .1       0
Bank Sta=171,181
XS Rating Curve= 0 ,0
Exp/Cntr=0.3,0.1

Type RM Length L Ch R = 1 ,1050    ,300.6,301.5,302.5
XS GIS Cut Line= 3
     1818802.202      152039.054      1818814.43      152141.716
      1818871.34      152303.339
#Sta/Elev= 30
     9.4 1558.93    18.8 1553.32    28.2 1547.75    37.6 1542.15      47  1536.4
    56.4 1530.53    65.8  1524.5    75.2 1518.39    84.6 1512.28      94 1506.21
   103.4 1500.14   113.5 1493.56   123.5 1486.89   133.6 1480.48   143.7 1476.62
   153.8 1476.06   158.9 1476.04   163.9 1476.01   168.9 1476.27   173.9 1476.53
     184 1477.41   194.1 1478.36   204.2 1479.25   214.3 1480.27   224.3 1482.33
   234.4 1486.71   244.5 1493.25   254.6 1500.73   264.7 1508.18   274.7 1514.82
#Mann= 3 , 0 , 0
       0      .1       0   158.9    .045       0   168.9      .1       0
Bank Sta=158.9,168.9
XS Rating Curve= 0 ,0
Exp/Cntr=0.3,0.1

Type RM Length L Ch R = 1 ,748.4   ,237.3,240.4,243.5
XS GIS Cut Line= 4
     1818507.743      152127.615     1818532.419      152234.544
     1818557.095      152316.798     1818604.097      152436.653
#Sta/Elev= 23
      10 1538.82      20 1533.57    29.9 1528.21    39.9 1522.67    79.8 1499.67
    89.8 1493.72    99.8 1487.38   109.7 1480.49   119.3 1473.66   128.8  1467.8
   133.4 1466.61   138.4 1465.31   143.4 1465.59   147.9 1465.85     167 1468.08
   186.1 1470.05   195.6 1471.65   205.5 1474.75   215.4 1479.24   245.1  1494.4
   274.8 1509.14   284.7 1514.15   324.4 1534.46
#Mann= 3 , 0 , 0
       0     .06       0   133.4    .045       0   143.4     .06       0
Bank Sta=133.4,143.4
XS Rating Curve= 0 ,0
Exp/Cntr=0.3,0.1

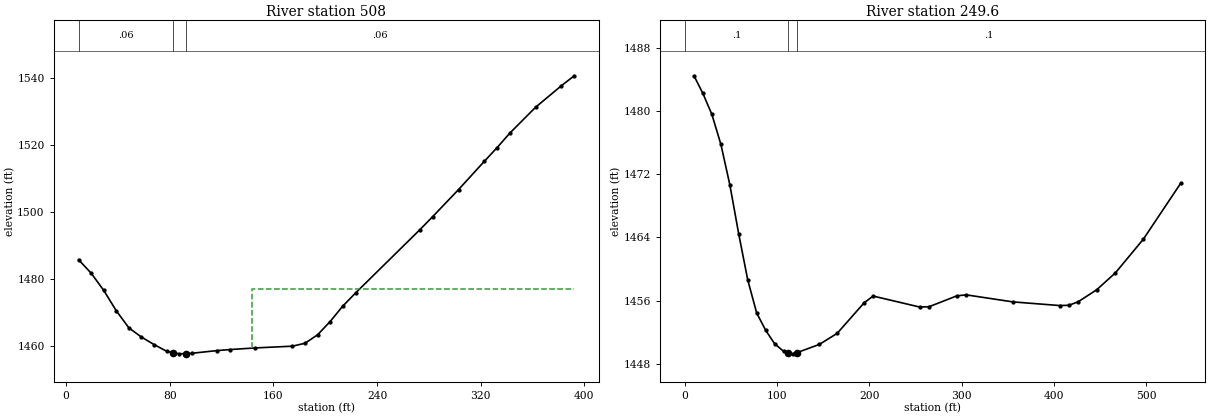
Type RM Length L Ch R = 1 ,508     ,242.7,258.4,274.2
XS GIS Cut Line= 3
     1818292.709      152206.343     1818322.085      152417.852
     1818467.791      152521.256
#Sta/Elev= 30
     9.7 1485.79    19.4 1481.77    29.1 1476.62    38.8 1470.52    48.5 1465.43
    58.2 1462.68    67.9 1460.45    77.7 1458.42    82.4 1458.06    87.4 1457.67
    92.4 1457.76    97.1 1457.84   116.5 1458.64   126.2 1458.94   145.6 1459.43
   174.7 1459.96   184.4 1460.83   194.1 1463.35   203.8 1467.32   213.5 1471.91
   223.5 1475.89   273.1 1494.79     283  1498.7   302.9 1506.77   322.7 1515.17
   332.7 1519.33   342.6 1523.69   362.4 1531.39   382.3 1537.82   392.2 1540.79
#Mann= 3 , 0 , 0
     9.7     .06       0    82.4    .045       0    92.4     .06       0
#XS Ineff= 2 , 0
                          143.62          1477.2
Permanent Ineff=
       F       F
Bank Sta=82.4,92.4
XS Rating Curve= 0 ,0
Exp/Cntr=0.3,0.1

Type RM Length L Ch R = 1 ,249.6   ,265.5,249.6,233.7
XS GIS Cut Line= 3
     1818143.477      152161.691     1818021.272      152325.023
     1818244.532      152572.959
#Sta/Elev= 30
     9.7 1484.44    19.4  1482.2    29.1 1479.56    38.9 1475.76    48.6 1470.65
    58.3 1464.39      68 1458.63    77.7 1454.44    87.4 1452.26    97.1 1450.56
   106.9 1449.59   111.6 1449.43   116.6 1449.27   121.6 1449.43   145.7 1450.46
   165.1 1451.87   194.3 1455.73     204 1456.58   254.5 1455.19   264.7 1455.23
     295 1456.61   305.1 1456.73   355.6 1455.84   406.2 1455.38   416.3 1455.41
   426.4 1455.85   446.6 1457.38   466.9 1459.52   497.2 1463.78   537.6 1470.83
#Mann= 3 , 0 , 0
       0      .1       0   111.6    .045       0   121.6      .1       0
Bank Sta=111.6,121.6
XS Rating Curve= 0 ,0
Exp/Cntr=0.3,0.1

Chan Stop Cuts=-1
Use User Specified Reach Order=0